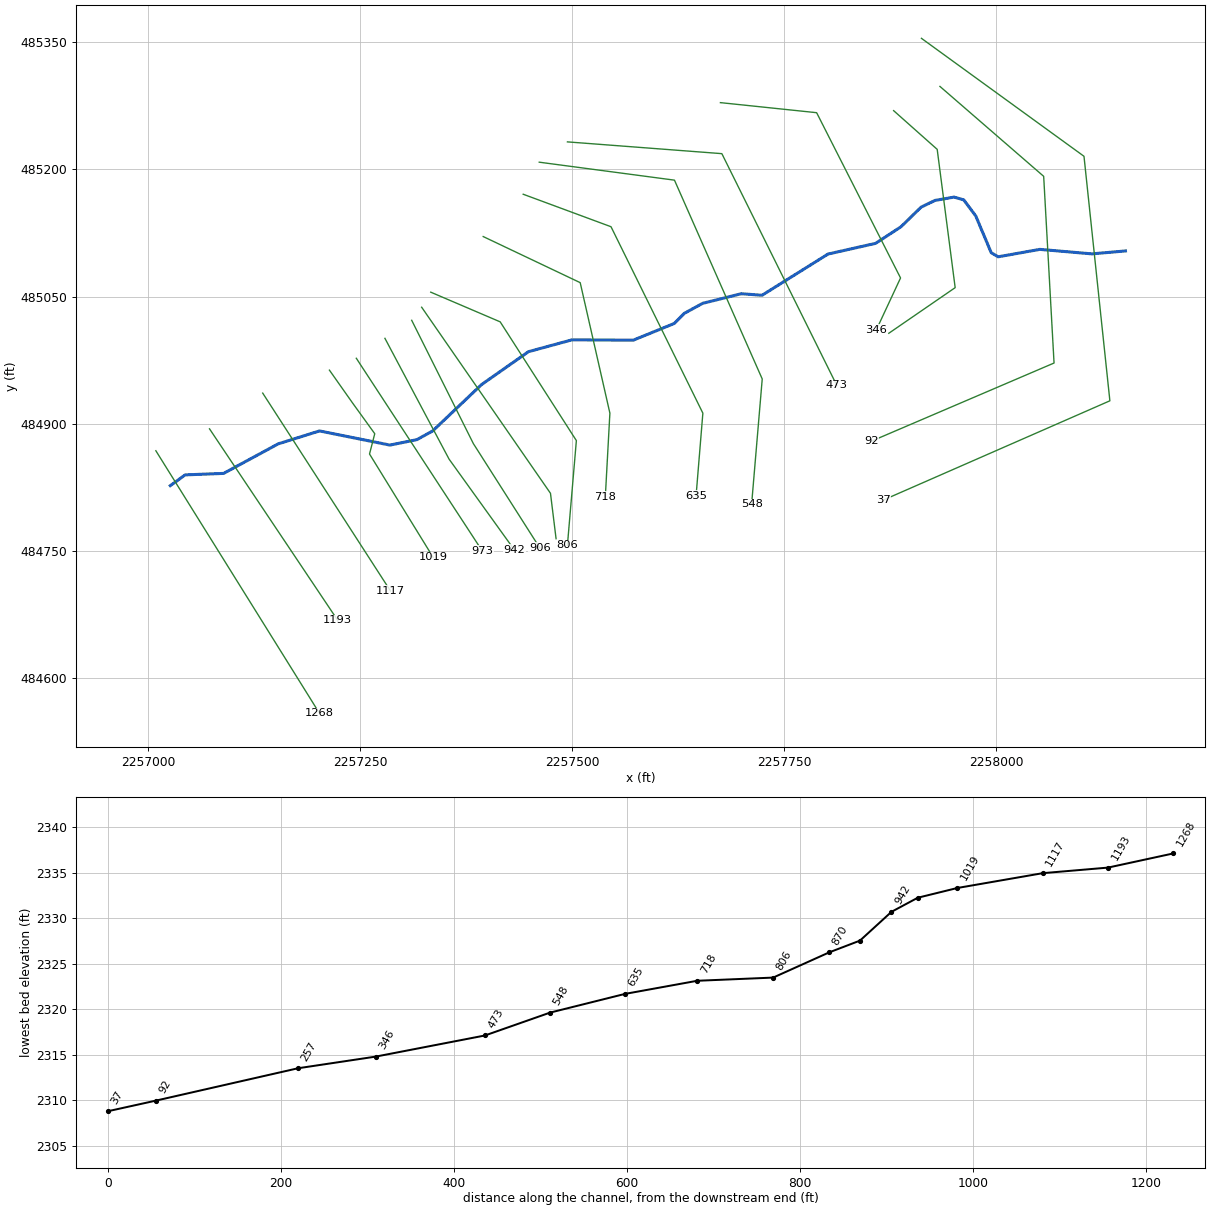
--- CLOVERCKT1.prj (project) ---

Proj Title=CLOVERCKT1
Current Plan=p01
Default Exp/Contr=0,0
English Units
Geom File=g01
Flow File=f01
Plan File=p01
Background Map Layer=Inundation Boundary (01pct Value_0)
BEGIN DESCRIPTION:
----------MODEL BY WOOD PLC 2021----------
Stream Name: Clover Creek Tributary I
Flood Zone: Enhanced Approximate
Pocahontas County, WV
HEC-RAS Version: RAS 6.1
Vertical Datum: NAVD88
Projection: NAD 1983 StatePlane West Virginia S FIPS 4702 (US Feet)
Terrain: 1-meter LIDAR (FEMA Region III 3DEP collected 2016-2018)
Land Use: 2019 NLCD
Hydrologic Method:
WV SIR2010-5033 regression equations
END DESCRIPTION:
DSS File=dss
DSS Export Rating Curves= 0
DSS Export Rating Curve Sorted= 0
DSS Export Volume Flow Curves= 0
DXF OffsetX= 0
DXF OffsetY= 0
DXF ScaleX= 0
DXF ScaleY= 0

--- CLOVERCKT1.p01 (plan) ---

Plan Title=Floodplain
Program Version=6.10
Short Identifier=Floodplain
Geom File=g01
Flow File=f01
Subcritical Flow
K Sum by GR= 0
Std Step Tol= 0.01
Critical Tol= 0.01
Num of Std Step Trials= 20
Max Error Tol= 0.3
Flow Tol Ratio= 0.001
Split Flow NTrial= 30
Split Flow Tol= 0.02
Split Flow Ratio= 0.02
Log Output Level= 0
Friction Slope Method= 1
Unsteady Friction Slope Method= 2
Unsteady Bridges Friction Slope Method= 1
Parabolic Critical Depth
Global Vel Dist= 0 , 0 , 0
Global Log Level= 0
CheckData=True
Encroach Param=-1 ,0,0, 0
Computation Interval=0.1SEC
Output Interval=1SEC
Instantaneous Interval=Max Profile
Mapping Interval=1HOUR
Computation Time Step Use Courant=        0
Computation Time Step Use Time Series=    0
Computation Time Step Count To Double=0
Computation Time Step Max Doubling=0
Computation Time Step Max Halving=0
Computation Time Step Residence Courant=0
Run HTab= 0
Run UNet= 0
Run Sediment= 0
Run PostProcess= 0
Run WQNet= 0
Run RASMapper=-1
UNET Theta= 0
UNET Theta Warmup= 0
UNET ZTol= 0
UNET ZSATol= 0
UNET MxIter= 0
UNET Max Iter WO Improvement= 0
UNET MaxInSteps= 0
UNET DtIC= 0
UNET DtMin= 0
UNET MaxCRTS= 0
UNET WFStab= 0
UNET SFStab= 0
UNET WFX= 1
UNET SFX= 1
UNET Gravity=32.174
UNET 1D Methodology=Finite Difference
UNET DSS MLevel= 1
UNET Pardiso=0
UNET DZMax Abort= 0
UNET Use Existing IB Tables= 0
UNET Froude Reduction=False
UNET Froude Limit= 0
UNET Froude Power= 0
UNET D1 Cores= 0
UNET WindReference=Eulerian
UNET WindDragFormulation=Hsu (1988)
UNET D2 Coriolis=0
UNET D2 Cores= 0
UNET D2 Theta= 1
UNET D2 Theta Warmup= 1
UNET D2 Z Tol= 0.01
UNET D2 Volume Tol= 0.01
UNET D2 Max Iterations= 20
UNET D2 Equation= 0
UNET D2 RampUpFraction=0.1
UNET D2 TimeSlices= 1
UNET D2 Turbulence Formulation=Non-Conservative (original)
UNET D2 Eddy Viscosity=0.3
UNET D2 Transverse Eddy Viscosity=0.1
UNET D2 Smagorinsky Mixing=0
UNET D2 BCVolumeCheck=0
UNET D2 Cores=0
UNET D2 SolverType=PARDISO (Direct)
UNET D2 Minimum Iterations= 2147483647
UNET D2 Maximum Iterations= 2147483647
UNET D2 Restart Number= 10
UNET D2 Relaxation Coeff=1.3
UNET D2 SOR Precondition Iterations= 10
UNET D2 ILUT Maximum Fill= 8
UNET D2 ILUT Tolerance=1E-08
UNET D1D2 MaxIter= 0
UNET D1D2 ZTol=0.01
UNET D1D2 QTol=0.1
UNET D1D2 MinQTol=1
DSS File=dss
Write IC File= 0
Write IC File at Fixed DateTime=0
Write IC File at Sim End=0
Echo Input=False
Echo Parameters=False
Echo Output=False
Write Detailed= 0
HDF Write Warmup=0
HDF Write Time Slices=0
HDF Flush=0
HDF Compression= 1
HDF Chunk Size= 1
HDF Spatial Parts= 1
HDF Use Max Rows=0
HDF Fixed Rows= 1
Calibration Method= 0
Calibration Iterations= 20
Calibration Max Change=0.05
Calibration Tolerance=0.2
Calibration Maximum=1.5
Calibration Minimum=0.5
Calibration Optimization Method= 1
WQ AD Non Conservative
WQ ULTIMATE=-1
WQ Max Comp Step=1HOUR
WQ Output Interval=15MIN
WQ Output Selected Increments= 0
WQ Output face flow=0
WQ Output face velocity=0
WQ Output face area=0
WQ Output face dispersion=0
WQ Output cell volume=0
WQ Output cell surface area=0
WQ Output cell continuity=0
WQ Output cumulative cell continuity=0
WQ Output face conc=0
WQ Output face dconc_dx=0
WQ Output face courant=0
WQ Output face peclet=0
WQ Output face adv mass=0
WQ Output face disp mass=0
WQ Output cell mass=0
WQ Output cell source sink temp=0
WQ Output nsm pathways=0
WQ Output nsm derived pathways=0
WQ Create Restart=0
WQ Fixed Restart=0
WQ System Summary=0
WQ Write To DSS=0
Sorting and Armoring Iterations= 10
XS Update Threshold= 0.02
Bed Roughness Predictor= 0
Hydraulics Update Threshold= 0.02
Energy Slope Method= 1
Volume Change Method= 1
Sediment Retention Method= 0
Sediment TS Multiplier= 1
Warm Up Method= 0
XS Weighting Method= 0
Number of US Weighted Cross Sections= 1
Number of DS Weighted Cross Sections= 1
Upstream XS Weight=0
Main XS Weight=1
Downstream XS Weight=0
Number of DS XS's Weighted with US Boundary= 1
Upstream Boundary Weight= 1
Weight of XSs Associated with US Boundary= 0
Number of US XS's Weighted with DS Boundary= 1
Downstream Boundary Weight= 0.5
Weight of XSs Associated with DS Boundary= 0.5
Percentile Method= 0
Sediment Output Level= 3
Mass or Volume Output= 0
Output Increment Type= 1
Profile and TS Output Increment= 1
Transport Output Increment 1
XS Output Flag= 0
XS Output Increment= 10
Read HDF5 Sediment Hotstart= 0
Sediment Hotstart Type= 0
Write Gradation File= 0
Read Gradation Hotstart= 0
Write HDF5 File= 1
Write Binary Output= 1
Write DSS Sediment File= 0
DSS Sediment Output Type= 1
SV Curve= 0
Specific Gage Flag= 0
Subcell Erosion Methods= 0
Subcell Deposition Methods= 0
Advection Scheme= 1
Matrix Solver= 0
Implicit Weighting Factor= 1
Maximum Outer Loop Convergence Iterations= 5
Convergence Maximum Absolute= 0.001
Convergence RMSE= 0.0001
Grain Fractions Max Abs Error= 0.001
Max Subgrid Regions= 1
Max Subgrid Length Scale= 3.402823E+38
Initial Layer Thickness= 3.402823E+38
Min Layer Thickness= 3.402823E+38
Max Layer Thickness= 3.402823E+38
Number of Layers= 5

--- CLOVERCKT1.f01 (steady flow) ---

Flow Title=Flow
Program Version=6.10
Number of Profiles= 6
Profile Names=01pct,10pct,04pct,02pct,0_2pct,01plus
River Rch & RM=CLOVERCKT1,Main,1268
     528     278     370     446     738     780
Boundary for River Rch & Prof#=CLOVERCKT1,Main            , 1
Up Type= 0
Dn Type= 3
Dn Slope=0.02327
Boundary for River Rch & Prof#=CLOVERCKT1,Main            , 2
Up Type= 0
Dn Type= 3
Dn Slope=0.02327
Boundary for River Rch & Prof#=CLOVERCKT1,Main            , 3
Up Type= 0
Dn Type= 3
Dn Slope=0.02327
Boundary for River Rch & Prof#=CLOVERCKT1,Main            , 4
Up Type= 0
Dn Type= 3
Dn Slope=0.02327
Boundary for River Rch & Prof#=CLOVERCKT1,Main            , 5
Up Type= 0
Dn Type= 3
Dn Slope=0.02327
Boundary for River Rch & Prof#=CLOVERCKT1,Main            , 6
Up Type= 0
Dn Type= 3
Dn Slope=0.02327
DSS Import GetInterval= 0
DSS Import GetPeak= 0
DSS Import FillOption= 0

--- CLOVERCKT1.g01 (geometry) ---

Geom Title=Geometry
Program Version=6.10

River Reach=CLOVERCKT1      ,Main
Reach XY= 30
     2257026.237      484827.042     2257043.748      484839.763
     2257089.084      484841.507     2257153.478      484876.348
     2257202.188      484891.597     2257285.219      484874.918
2257316.93644828484881.279206883     2257335.641      484891.555
     2257393.327      484946.287     2257448.618      484985.058
     2257499.902      484999.014     2257572.263      484998.652
     2257620.491      485018.301     2257632.335      485030.212
     2257654.124      485042.112     2257699.614      485053.408
     2257724.129      485051.601     2257801.896      485100.197
     2257858.021      485112.821     2257887.912      485132.331
     2257911.759      485155.567     2257928.093      485163.469
     2257950.538      485167.359     2257961.966        485164.1
     2257976.181      485145.069     2257994.412      485101.772
     2258002.504      485096.939     2258051.719      485105.726
     2258113.092       485100.43     2258152.722      485103.867

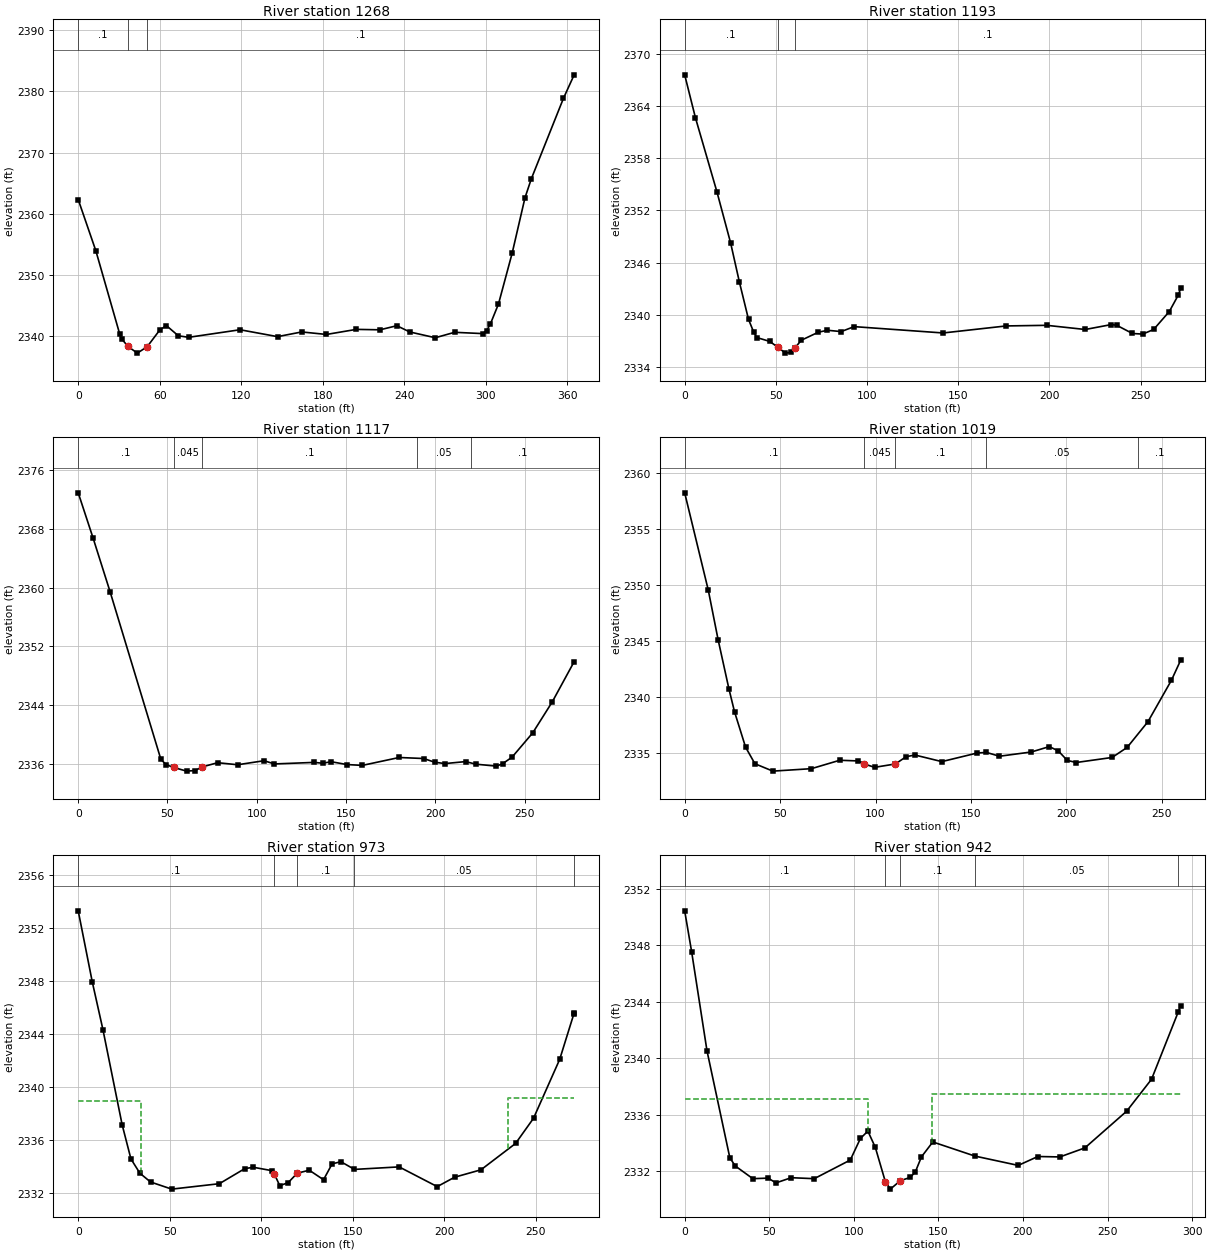
Type RM Length L Ch R = 1 ,1268    ,75.8,75.7,74.4
XS GIS Cut Line= 2
2257009.19180342484868.2249093022257202.21969512484558.499546954
#Sta/Elev= 30
       0  2362.3      13 2353.89    30.5  2340.3    31.9  2339.5    36.6 2338.24
    43.5 2337.14    50.8  2338.2    60.1 2340.95    64.9 2341.65    73.7 2339.98
    81.3 2339.73   119.1 2340.97   146.7 2339.84   164.5 2340.61   182.7  2340.2
   204.7 2341.03   222.1 2340.96   234.5 2341.63     244 2340.61   262.8 2339.66
     277 2340.55   297.6 2340.34   300.6 2340.83   303.4 2341.95   309.3 2345.18
   319.4 2353.54   328.8 2362.58   333.5 2365.71   357.1 2378.87     365 2382.73
#Mann= 3 ,-1,0
       0      .1       0    36.6    .045       0    50.8      .1       0
Bank Sta=36.6,50.8
XS Rating Curve= 0 ,0
Exp/Cntr(USF)=0,0
Exp/Cntr=0.3,0.1

Type RM Length L Ch R = 1 ,1193    ,75.2,75.3,75.2
XS GIS Cut Line= 2
2257072.46110036484894.0795540312257223.72744439 484668.17086557
#Sta/Elev= 30
       0 2367.61     5.9 2362.67    17.7 2354.13    25.2 2348.25      30 2343.76
      35 2339.46    37.9 2337.97    39.6 2337.37    46.6 2336.93    50.92336.286
    55.2 2335.58    58.1 2335.66    60.5 2336.19    63.9 2337.06    73.3 2337.99
    78.3 2338.21    85.8 2338.06    92.9 2338.63   141.7  2337.9   176.3 2338.71
   198.5 2338.78   219.6  2338.3     234 2338.87   236.9 2338.78   245.5 2337.84
   251.1 2337.77   257.1  2338.3   265.7 2340.37   270.7 2342.29   271.9 2343.03
#Mann= 3 ,-1,0
       0      .1       0    50.9    .045       0    60.5      .1       0
Bank Sta=50.9,60.5
XS Rating Curve= 0 ,0
Exp/Cntr(USF)=0,0
Exp/Cntr=0.3,0.1

Type RM Length L Ch R = 1 ,1117    ,107.2,98.8,89.4
XS GIS Cut Line= 2
2257135.21351382484936.208074882 2257285.9660954484702.813133586
#Sta/Elev= 30
       0 2372.93     8.4 2366.71    17.9  2359.4    46.3 2336.58    49.2 2335.86
    53.4 2335.48    60.7 2334.97    65.5 2335.05    69.4 2335.54    78.1 2336.12
    89.3 2335.84   104.1 2336.39   109.9 2335.95   132.2 2336.16   136.9 2336.05
   141.8 2336.25   150.4 2335.87   159.1 2335.75   179.8 2336.83   193.5 2336.69
   199.6 2336.19   205.4    2336     217 2336.27   222.7 2335.92   234.3 2335.65
   237.7 2335.98     243 2336.87   254.6 2340.19   265.5  2344.4   277.8  2349.9
#Mann= 5 ,-1,0
       0      .1       0    53.4    .045       0    69.4      .1       0
     190     .05       0     220      .1       0
Bank Sta=53.4,69.4
XS Rating Curve= 0 ,0
Exp/Cntr(USF)=0,0
Exp/Cntr=0.3,0.1

Type RM Length L Ch R = 1 ,1019    ,37,45.7,53.9
XS GIS Cut Line= 5
2257213.89256321484963.2906954282257241.56234085484924.024565367
2257267.34668034484888.3381225372257261.18483077484864.388430085
2257336.15692622484742.627010678
#Sta/Elev= 30
       0  2358.2    12.4 2349.48    17.5 2345.09    23.2 2340.67    26.1 2338.65
    31.9 2335.48    36.8    2334    46.2 2333.34    66.4 2333.56    81.2 2334.31
      91 2334.25   93.68    2334    99.5 2333.68   110.4 2333.98     116 2334.63
   120.6 2334.78   134.7 2334.19   153.3 2334.96   158.1 2335.01   164.9 2334.67
   181.6 2335.05     191 2335.53   195.7 2335.15   200.4  2334.3   205.1 2334.11
   223.9 2334.56   231.8 2335.46   242.7 2337.76     255 2341.46   259.8 2343.24
#Mann= 5 ,-1,0
       0      .1       0   93.68    .045       0   110.4      .1       0
  157.65     .05       0  237.65      .1       0
Bank Sta=93.68,110.4
XS Rating Curve= 0 ,0
Exp/Cntr(USF)=0,0
Exp/Cntr=0.3,0.1

Type RM Length L Ch R = 1 ,973     ,32.5,30.4,29.7
BEGIN DESCRIPTION:
structurexs 4
END DESCRIPTION:
XS GIS Cut Line= 2
2257245.59904581484977.3090708332257393.85620977484750.519646744
#Sta/Elev= 30
       0 2353.29     7.7 2347.91    13.5 2344.32      24 2337.13    28.8 2334.55
    33.7 2333.47    39.5 2332.81    51.1 2332.27    77.1 2332.68      91 2333.82
    95.7 2333.92     106 2333.66   107.1 2333.42   110.1 2332.53   114.7 2332.76
   119.6 2333.47   126.2  2333.7     134 2332.98   138.7 2334.18   143.5 2334.34
   150.9 2333.76   175.3 2333.95   196.1 2332.46   205.6 2333.17     220 2333.73
   238.9 2335.72   248.7 2337.62     263 2342.07   270.7 2345.49   270.9 2345.58
#Mann= 5 ,-1,0
       0      .1       0   107.1    .045       0   119.6      .1       0
   150.9     .05       0   270.7      .1       0
#XS Ineff= 2 , 0
           34.39  2338.9  234.72         2339.15
Permanent Ineff=
       F       F
Bank Sta=107.1,119.6
XS Rating Curve= 0 ,0
Exp/Cntr(USF)=0,0
Exp/Cntr=0.5,0.3

Type RM Length L Ch R = 1 ,942     ,37.7,36.4,36.7
BEGIN DESCRIPTION:
structure xs 3
END DESCRIPTION:
XS GIS Cut Line= 3
2257279.36057819485000.7953542342257354.95705289484858.409761116
 2257432.0214203  484751.2535931
#Sta/Elev= 30
       0 2350.43     4.1 2347.54    13.2 2340.51    26.7 2332.94    29.9 2332.36
    40.3 2331.46    49.4  2331.5    53.9 2331.16      63 2331.53    76.6 2331.46
    97.9 2332.78   103.9 2334.31   108.3 2334.83   112.7 2333.68   118.6 2331.26
   121.6 2330.72   127.5 2331.32   133.4 2331.55   136.4 2331.95     140 2333.01
   146.7 2334.06   171.6 2333.06   197.2  2332.4   208.8 2333.03   221.8    2333
   236.6 2333.64   261.3 2336.24     276  2338.5   291.9  2343.3   293.2 2343.71
#Mann= 5 ,-1,0
       0      .1       0   118.6    .045       0   127.5      .1       0
   171.6     .05       0   291.9      .1       0
#XS Ineff= 2 , 0
          108.64 2337.07  146.01         2337.44
Permanent Ineff=
       F       F
Bank Sta=118.6,127.5
XS Rating Curve= 0 ,0
Exp/Cntr(USF)=0,0
Exp/Cntr=0.5,0.3

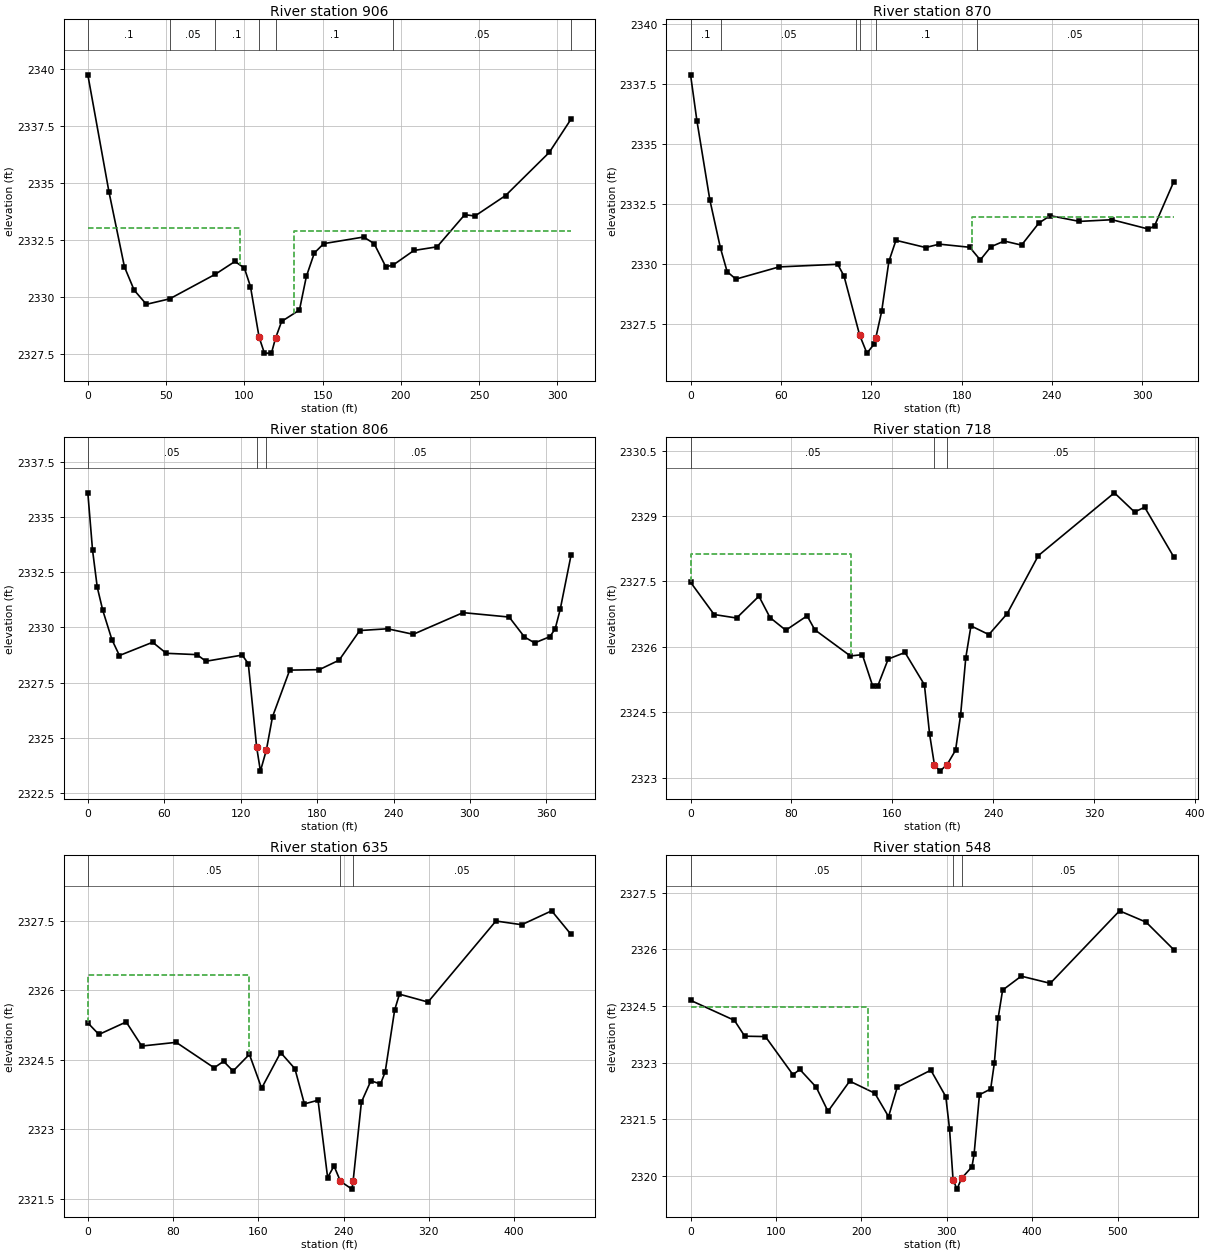
Type RM Length L Ch R = 1 ,906     ,33.2,35.5,36.2
BEGIN DESCRIPTION:
structure xs 2
END DESCRIPTION:
XS GIS Cut Line= 3
2257310.92027151485022.0797985662257383.58096079484876.758420023
2257462.11322091484753.455432169
#Sta/Elev= 30
       0 2339.76    13.5 2334.63    23.4 2331.34    29.6 2330.32    37.4  2329.7
    52.3 2329.94    81.5 2331.02      94 2331.58     100 2331.29   103.9 2330.48
   109.42328.262   112.8 2327.56   117.3 2327.56   119.92328.213   123.8 2328.95
   135.2 2329.45   139.6 2330.92   144.7 2331.95   150.7 2332.36   176.2 2332.65
   182.9 2332.36   190.4 2331.34   195.2 2331.43   208.3 2332.06   223.1 2332.22
   240.8 2333.63   247.3 2333.57   266.9 2334.47   294.8 2336.36   308.7 2337.82
#Mann= 7 ,-1,0
       0      .1       0    52.3     .05       0    81.5      .1       0
   109.4    .045       0   119.9      .1       0   195.2     .05       0
   308.7      .1       0
#XS Ineff= 2 , 0
           97.09 2333.03   131.4          2332.9
Permanent Ineff=
       F       F
Bank Sta=109.4,119.9
XS Rating Curve= 0 ,0
Exp/Cntr(USF)=0,0
Exp/Cntr=0.5,0.3

Type RM Length L Ch R = 1 ,870     ,65.1,64.8,64.6
XS GIS Cut Line= 3
2257322.66341321485037.4926720482257474.59030896484818.042711521
2257481.19582617484764.464627513
#Sta/Elev= 30
       0 2337.89     4.2 2335.98    12.8 2332.67    19.8 2330.67    24.3 2329.67
    30.1 2329.36    58.8 2329.87    97.7 2329.98   101.9 2329.49   112.3 2327.02
   117.1 2326.27   122.1 2326.66     1232326.905   126.9 2328.01   131.7  2330.1
   136.4 2330.98   156.1 2330.68   165.2 2330.82   185.4 2330.69   192.4 2330.16
   199.4 2330.71   208.3 2330.95   219.8 2330.78   231.3  2331.7   238.8 2332.01
   258.2 2331.77   279.9 2331.84   304.1 2331.45   308.1 2331.58   320.9 2333.43
#Mann= 6 ,-1,0
       0      .1       0      20     .05       0     110      .1       0
   112.3    .045       0     123      .1       0     190     .05       0
#XS Ineff= 2 , 0
                          187.21         2331.94
Permanent Ineff=
       F       F
Bank Sta=112.3,123
XS Rating Curve= 0 ,0
Exp/Cntr(USF)=0,0
Exp/Cntr=0.3,0.1

Type RM Length L Ch R = 1 ,806     ,90.5,87.7,84.6
XS GIS Cut Line= 4
2257333.37903002 485055.254173872257415.28744338485020.244932675
2257505.12247738484880.2079678982257494.55364985484756.684796137
#Sta/Elev= 30
       0 2336.09     3.7  2333.5     7.4 2331.82    11.7 2330.78    18.9 2329.45
    24.8 2328.73    50.9 2329.33    61.6 2328.83    85.7 2328.77    92.7 2328.47
   121.2 2328.75     126 2328.36   132.5 2324.61   135.5  2323.5   140.2 2324.46
     145 2325.96   158.5 2328.07   181.7 2328.09   197.3 2328.52   213.5 2329.86
   235.3 2329.94   255.5 2329.69   294.6 2330.67   330.8 2330.47   342.8 2329.57
   350.8  2329.3   362.7 2329.58   366.9 2329.93   370.9 2330.82   379.4 2333.27
#Mann= 3 ,-1,0
       0     .05       0   132.5    .045       0   140.2     .05       0
Bank Sta=132.5,140.2
XS Rating Curve= 0 ,0
Exp/Cntr(USF)=0,0
Exp/Cntr=0.3,0.1

Type RM Length L Ch R = 1 ,718     ,80.1,83.4,85
XS GIS Cut Line= 4
2257395.25191292485120.8418217442257509.64847991485066.467243202
2257544.65772111 484912.558692292257539.27997836484814.060070924
#Sta/Elev= 30
       0 2327.48    18.7 2326.74    36.5 2326.66    54.2 2327.16      63 2326.67
    75.5 2326.38    92.4 2326.71    98.5 2326.39   126.7 2325.79   136.2 2325.82
   144.4  2325.1   148.5 2325.11   156.7 2325.72     170 2325.87   185.4 2325.13
   189.5    2324   193.3  2323.3   197.7 2323.15   203.4  2323.3   210.1 2323.63
   214.1 2324.44   218.2 2325.75   222.3 2326.48   236.5 2326.28     251 2326.76
   275.7 2328.09     336 2329.53     352 2329.09     360  2329.2   383.1 2328.06
#Mann= 3 ,0,0
       0     .05       0   193.3    .045       0   203.4     .05       0
#XS Ineff= 2 , 0
          127.33 2328.12
Permanent Ineff=
       F       F
Bank Sta=193.3,203.4
XS Rating Curve= 0 ,0
Exp/Cntr(USF)=0,0
Exp/Cntr=0.3,0.1

Type RM Length L Ch R = 1 ,635     ,86.7,86.8,86
XS GIS Cut Line= 4
2257442.44055032485170.751307006 2257545.9969129485132.419571245
2257654.30930674484912.558692291 2257646.2893571484814.996179732
#Sta/Elev= 30
       0  2325.3    10.4 2325.05      36 2325.32    50.6  2324.8    82.9 2324.88
   118.5 2324.33   127.4 2324.47   136.3 2324.26   151.6 2324.62   163.1 2323.89
   180.9 2324.66   194.3 2324.31   203.2 2323.55     216 2323.63     225 2321.96
     231 2322.21     237 2321.88   247.8 2321.71   248.9 2321.88   256.7 2323.59
   265.6 2324.05   274.6 2323.98     279 2324.24   287.9 2325.58   292.4 2325.92
   319.2 2325.75   382.9  2327.5   407.1 2327.42   435.2 2327.72   453.4 2327.21
#Mann= 3 ,-1,0
       0     .05       0     237    .045       0   248.9     .05       0
#XS Ineff= 2 , 0
           151.1 2326.33
Permanent Ineff=
       F       F
Bank Sta=237,248.9
XS Rating Curve= 0 ,0
Exp/Cntr(USF)=0,0
Exp/Cntr=0.3,0.1

Type RM Length L Ch R = 1 ,548     ,73.8,75.2,75.3
XS GIS Cut Line= 4
2257461.35060323485208.5488690732257620.82744431485187.358442411
2257724.32778913 484952.852347252257711.77730643484804.888761825
#Sta/Elev= 30
       0 2324.65    51.3 2324.12    63.4  2323.7    87.6 2323.69   119.9 2322.68
   127.9 2322.82   147.1 2322.35   160.9 2321.71   186.3 2322.51   215.7 2322.19
   231.8 2321.57     242 2322.35   281.3  2322.8   298.8  2322.1   303.2 2321.24
   307.3  2319.9   311.9 2319.65   317.22319.934   329.4 2320.24   331.9 2320.57
   338.2 2322.15   351.3  2322.3   355.6 2322.98     360 2324.17   365.3 2324.92
   387.1 2325.29   421.1  2325.1   502.2 2327.02   533.3 2326.72   565.7 2325.99
#Mann= 3 ,-1,0
       0     .05       0   307.3    .045       0   317.2     .05       0
#XS Ineff= 2 , 0
          208.31 2324.47
Permanent Ineff=
       F       F
Bank Sta=307.3,317.2
XS Rating Curve= 0 ,0
Exp/Cntr(USF)=0,0
Exp/Cntr=0.3,0.1

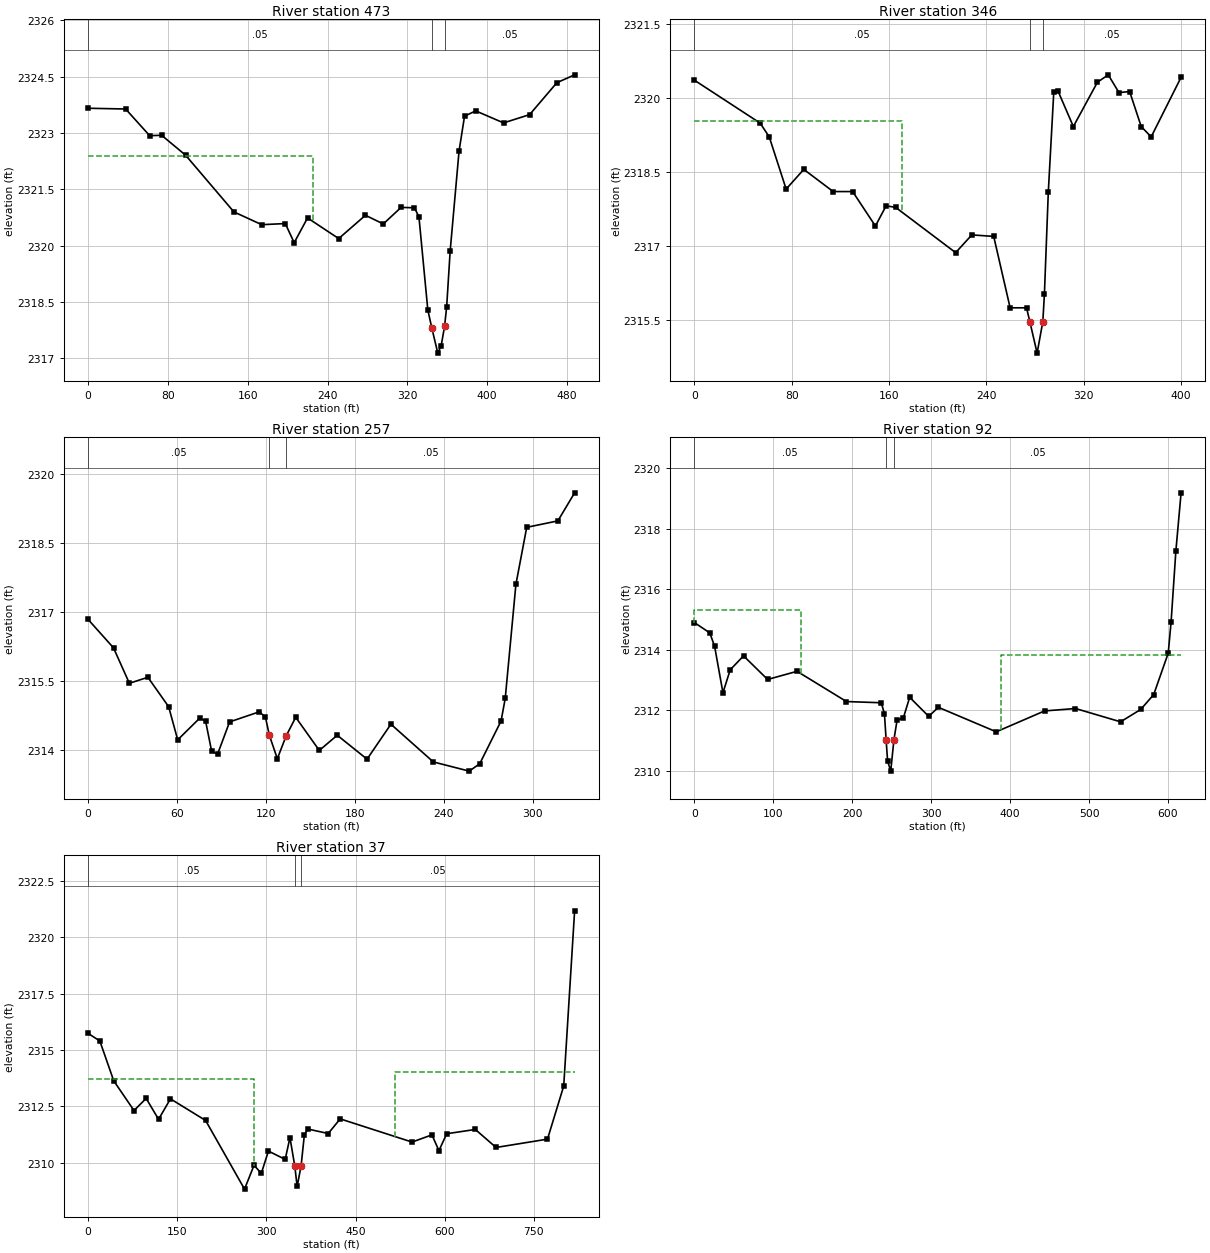
Type RM Length L Ch R = 1 ,473     ,125.8,126.2,125.9
XS GIS Cut Line= 3
2257494.58725761485232.4981672212257676.71353739 485218.61676566
2257812.23734658 484945.41321196
#Sta/Elev= 30
       0 2323.66    37.7 2323.64    61.8 2322.93    73.8 2322.94    97.8 2322.41
   146.2  2320.9   174.1 2320.56   197.7 2320.59   206.6 2320.08     220 2320.74
   251.2 2320.19     278 2320.81   295.9 2320.58   313.7 2321.02   327.1 2321.01
   331.6 2320.77   340.5 2318.29   344.5 2317.81   350.5 2317.14   353.9 2317.34
   357.32317.854   359.4 2318.38   362.9 2319.86   371.8 2322.52   377.3 2323.45
   388.5 2323.59   416.4 2323.27   442.5 2323.49   469.8 2324.34   487.6 2324.55
#Mann= 3 ,-1,0
       0     .05       0   344.5    .045       0   357.3     .05       0
#XS Ineff= 2 , 0
          225.08 2322.39
Permanent Ineff=
       F       F
Bank Sta=344.5,357.3
XS Rating Curve= 0 ,0
Exp/Cntr(USF)=0,0
Exp/Cntr=0.3,0.1

Type RM Length L Ch R = 1 ,346     ,93,89.8,85.6
XS GIS Cut Line= 4
2257674.99390415485278.7886225742257788.48572356485266.925083409
2257887.44419543485071.9963057522257858.90183713485010.834109396
#Sta/Elev= 30
       0 2320.36      54 2319.49    61.5 2319.21    75.4 2318.15    89.9 2318.55
   114.1  2318.1   130.1  2318.1   148.8  2317.4   157.6 2317.81   165.4 2317.78
   214.8 2316.86   228.1 2317.22   246.1 2317.19   259.6 2315.74   273.1 2315.74
   275.9 2315.45   281.8 2314.82   286.5 2315.46   287.8 2316.02     291 2318.09
   295.5 2320.12     299 2320.14   311.6 2319.42   331.4 2320.32   340.3 2320.47
   349.1 2320.11   357.9 2320.13   367.4 2319.42   375.6 2319.21   400.2 2320.42
#Mann= 3 ,-1,0
       0     .05       0   275.9    .045       0   286.5     .05       0
#XS Ineff= 2 , 0
          170.27 2319.54
Permanent Ineff=
       F       F
Bank Sta=275.9,286.5
XS Rating Curve= 0 ,0
Exp/Cntr(USF)=0,0
Exp/Cntr=0.3,0.1

Type RM Length L Ch R = 1 ,257     ,162.8,164.5,162.6
XS GIS Cut Line= 4
2257879.28923592485269.3463259952257930.66548086485223.678552716
 2257951.8683756485060.5793624322257873.58076426485006.756629639
#Sta/Elev= 30
       0 2316.84    17.2 2316.22    27.9 2315.45    40.4 2315.58    54.4 2314.94
    60.5 2314.22    75.3 2314.69    79.3 2314.63    83.4 2313.97    87.4 2313.91
    95.5 2314.61   115.6 2314.83   119.7 2314.71   122.3 2314.32   127.7 2313.81
   133.62314.303   140.1 2314.71     156 2313.99   168.1 2314.32   188.2  2313.8
   204.3 2314.56   232.9 2313.74   257.1 2313.54   264.2  2313.7   278.6 2314.63
   281.4 2315.12   288.6  2317.6   295.9 2318.84   316.9 2318.98   328.2 2319.59
#Mann= 3 ,-1,0
       0     .05       0   122.3    .045       0   133.6     .05       0
Bank Sta=122.3,133.6
XS Rating Curve= 0 ,0
Exp/Cntr(USF)=0,0
Exp/Cntr=0.3,0.1

Type RM Length L Ch R = 1 ,92      ,54.8,55.2,55.5
XS GIS Cut Line= 4
2257933.92746466485297.8886842952258056.25185738485191.874210611
2258068.48429665484971.6903037282257853.19336547484879.539261218
#Sta/Elev= 30
       0 2314.89    19.4 2314.55    25.5 2314.11    36.1 2312.57    45.3 2313.33
    62.2 2313.79    92.7 2313.01     130 2313.28   192.6 2312.28   236.7 2312.24
   240.7 2311.88  242.89    2311   244.7 2310.32   248.7 2309.98   252.7 2311.01
   256.7 2311.66   264.7 2311.74   272.7 2312.42   296.8 2311.79     309 2312.09
   382.4 2311.28   443.6 2311.97   482.8 2312.05   539.9 2311.61   565.5 2312.02
   581.9 2312.51   600.3 2313.88   603.9  2314.9     610 2317.26   616.6 2319.18
#Mann= 3 ,0,0
       0     .05       0  242.89    .045       0   252.7     .05       0
#XS Ineff= 2 , 0
          134.88 2315.32  388.37         2313.81
Permanent Ineff=
       F       F
Bank Sta=242.89,252.7
XS Rating Curve= 0 ,0
Exp/Cntr(USF)=0,0
Exp/Cntr=0.3,0.1

Type RM Length L Ch R = 1 ,37      ,,,
XS GIS Cut Line= 4
2257912.10069872485354.6156443582258103.79127742485215.512746543
2258134.32605987484927.1286900972257867.14671345484810.078690716
#Sta/Elev= 30
       0 2315.74    19.9  2315.4    43.3 2313.63    77.4 2312.31    97.8 2312.85
   118.7 2311.92   138.7 2312.83   197.8 2311.87   263.3 2308.82   279.3 2309.88
   291.5 2309.52   303.5 2310.51   331.7 2310.14   339.7 2311.11   347.8 2309.85
   351.8 2308.94  358.43 2309.85   363.9 2311.22   369.5 2311.49   404.1 2311.29
   424.2 2311.94   545.1 2310.91   578.5 2311.23   590.3 2310.53   603.4 2311.28
   651.5 2311.47   686.4 2310.67   772.9 2311.04   800.2  2313.4818.5339 2321.18
#Mann= 3 ,0,0
       0     .05       0   347.8    .045       0  358.43     .05       0
#XS Ineff= 2 , 0
          279.07 2313.72  516.61            2314
Permanent Ineff=
       F       F
Bank Sta=347.8,358.43
XS Rating Curve= 0 ,0
Exp/Cntr(USF)=0,0
Exp/Cntr=0.3,0.1
LCMann Table=0

Chan Stop Cuts=-1
Use User Specified Reach Order=0
Composite Channel Slope=5